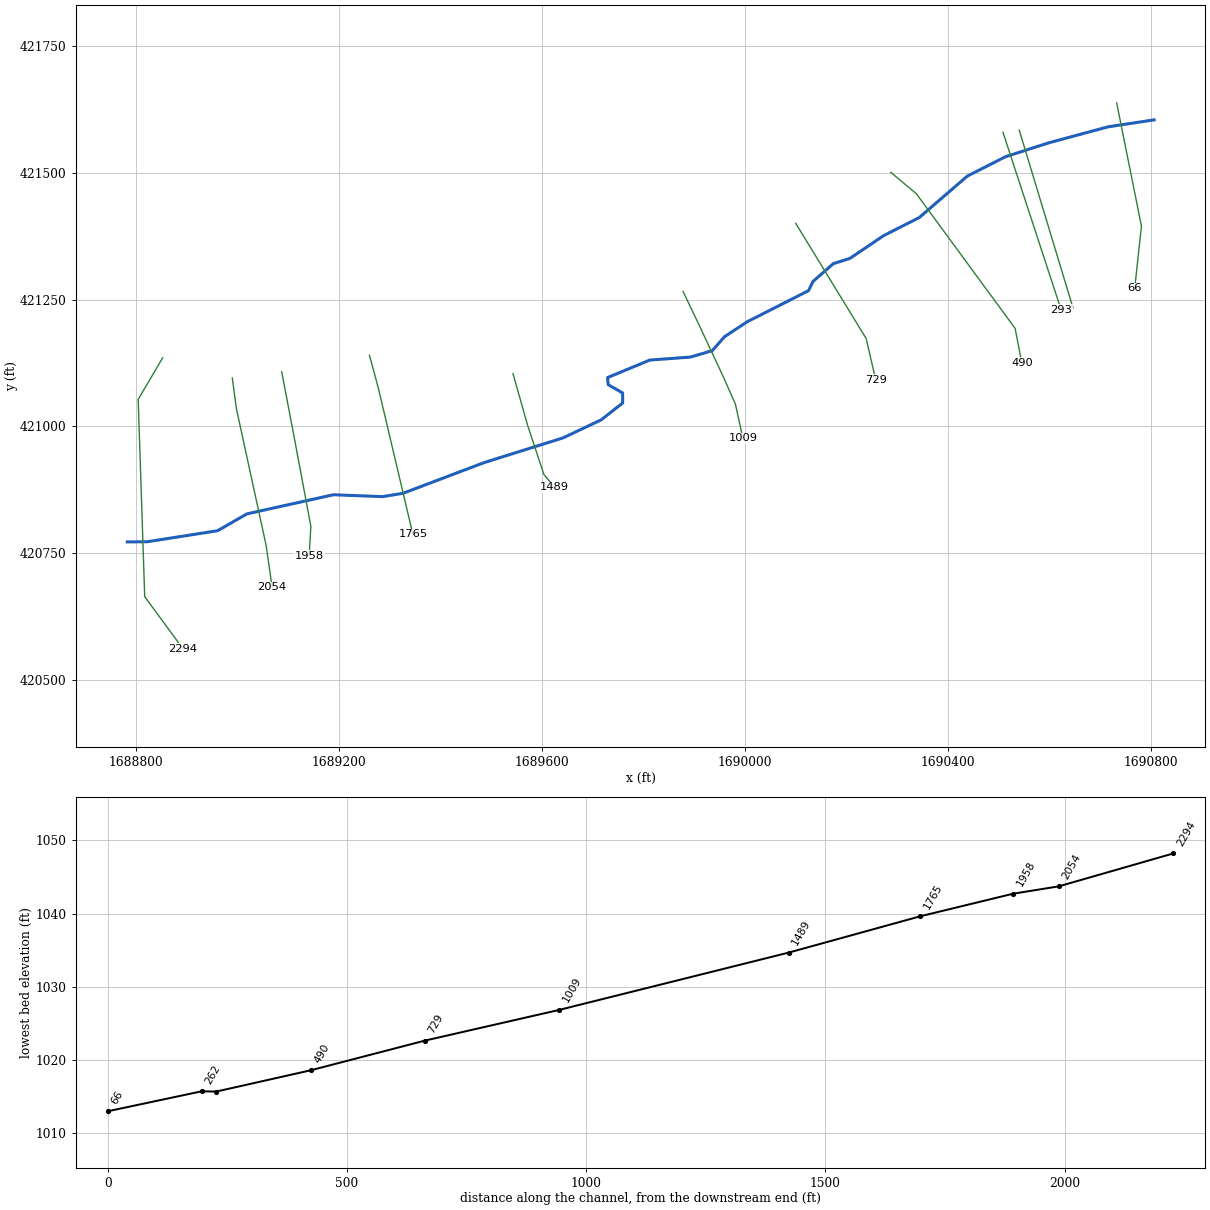
--- ROBERTSRN.prj (project) ---

Proj Title=ROBERTSRN
Current Plan=p01
Default Exp/Contr=0,0
English Units
Geom File=g01
Flow File=f01
Plan File=p01
BEGIN DESCRIPTION:
---------- MODELED AS PART OF WVEMD CTP PROGRAM, 2023----------
Stream Name: Roberts Run
Flood Zone:  AFH
Wetzel County, WV
HEC-RAS Version: RAS 6.3
Vertical Datum: NAVD88
Projection: NAD 1983 StatePlane West Virginia S FIPS 4702 (US Feet)
Terrain: 1-meter West Virginia FEMA R3 South Central (collected 2018-2020)
Land Use: 2019 NLCD
Hydrologic Method:
WV SIR2010-5033 regression equations
Additional Model Notes:
None
END DESCRIPTION:
DSS Export Rating Curves= 0
DSS Export Rating Curve Sorted= 0
DSS Export Volume Flow Curves= 0
DXF OffsetX= 0
DXF OffsetY= 0
DXF ScaleX= 0
DXF ScaleY= 0

--- ROBERTSRN.p01 (plan) ---

Plan Title=Floodplain
Program Version=6.30
Short Identifier=Floodplain
Geom File=g01
Flow File=f01
Subcritical Flow
K Sum by GR= 0
Std Step Tol= 0.01
Critical Tol= 0.01
Num of Std Step Trials= 20
Max Error Tol= 0.3
Flow Tol Ratio= 0.001
Split Flow NTrial= 30
Split Flow Tol= 0.02
Split Flow Ratio= 0.02
Log Output Level= 0
Friction Slope Method= 1
Unsteady Friction Slope Method= 2
Unsteady Bridges Friction Slope Method= 1
Parabolic Critical Depth
Global Vel Dist= 0 , 0 , 0
Global Log Level= 0
CheckData=False
Encroach Param=-1 ,0,0, 0
Mapping Interval=1HOUR
Computation Time Step Use Courant=        0
Computation Time Step Use Time Series=    0
Computation Time Step Count To Double=0
Computation Time Step Max Doubling=0
Computation Time Step Max Halving=0
Computation Time Step Residence Courant=0
Run HTab= 0
Run UNet= 0
Run Sediment= 0
Run PostProcess= 0
Run WQNet= 0
Run RASMapper=-1
UNET Theta= 0
UNET Theta Warmup= 0
UNET ZTol= 0
UNET ZSATol= 0
UNET MxIter= 0
UNET Max Iter WO Improvement= 0
UNET MaxInSteps= 0
UNET DtIC= 0
UNET DtMin= 0
UNET MaxCRTS= 0
UNET WFStab= 0
UNET SFStab= 0
UNET WFX= 1
UNET SFX= 1
UNET Gravity=32.17405
UNET 1D Methodology=Finite Difference
UNET DSS MLevel= 1
UNET Pardiso=0
UNET DZMax Abort= 0
UNET Use Existing IB Tables= 0
UNET Froude Reduction=False
UNET Froude Limit= 0
UNET Froude Power= 0
UNET D1 Cores= 0
UNET WindReference=Eulerian
UNET WindDragFormulation=Hsu (1988)
UNET D2 Coriolis=0
UNET D2 Cores= 0
UNET D2 Theta= 1
UNET D2 Theta Warmup= 1
UNET D2 Z Tol= 0.01
UNET D2 Volume Tol= 0.01
UNET D2 Max Iterations= 20
UNET D2 Equation= 0
UNET D2 RampUpFraction=0.1
UNET D2 TimeSlices= 1
UNET D2 Turbulence Formulation=Non-Conservative (original)
UNET D2 Eddy Viscosity=0.3
UNET D2 Transverse Eddy Viscosity=0.1
UNET D2 Smagorinsky Mixing=0
UNET D2 BCVolumeCheck=0
UNET D2 Cores=0
UNET D2 SolverType=PARDISO (Direct)
UNET D2 Minimum Iterations= 3
UNET D2 Maximum Iterations= 30
UNET D2 Restart Number= 10
UNET D2 Relaxation Coeff=1.3
UNET D2 SOR Precondition Iterations= 10
UNET D2 ILUT Maximum Fill= 8
UNET D2 ILUT Tolerance=1E-08
UNET D2 Convergence Tolerance=0.00001
UNET D1D2 MaxIter= 0
UNET D1D2 ZTol=0.01
UNET D1D2 QTol=0.1
UNET D1D2 MinQTol=1
Write IC File= 0
Write IC File at Fixed DateTime=0
Write IC File at Sim End=0
Echo Input=False
Echo Parameters=False
Echo Output=False
Write Detailed= 0
HDF Write Warmup=0
HDF Write Time Slices=0
HDF Flush=0
HDF Compression= 1
HDF Chunk Size= 1
HDF Spatial Parts= 1
HDF Use Max Rows=0
HDF Fixed Rows= 1
Calibration Method= 0
Calibration Iterations= 20
Calibration Max Change=0.05
Calibration Tolerance=0.2
Calibration Maximum=1.5
Calibration Minimum=0.5
Calibration Optimization Method= 1
WQ AD Non Conservative
WQ ULTIMATE=-1
WQ Max Comp Step=1HOUR
WQ Output Interval=15MIN
WQ Output Selected Increments= 0
WQ Output face flow=0
WQ Output face velocity=0
WQ Output face area=0
WQ Output face dispersion=0
WQ Output cell volume=0
WQ Output cell surface area=0
WQ Output cell continuity=0
WQ Output cumulative cell continuity=0
WQ Output face conc=0
WQ Output face dconc_dx=0
WQ Output face courant=0
WQ Output face peclet=0
WQ Output face adv mass=0
WQ Output face disp mass=0
WQ Output cell mass=0
WQ Output cell source sink temp=0
WQ Output nsm pathways=0
WQ Output nsm derived pathways=0
WQ Create Restart=0
WQ Fixed Restart=0
WQ System Summary=0
WQ Write To DSS=0
Sorting and Armoring Iterations= 10
XS Update Threshold= 0.02
Bed Roughness Predictor= 0
Hydraulics Update Threshold= 0.02
Energy Slope Method= 1
Volume Change Method= 1
Sediment Retention Method= 0
Sediment TS Multiplier= 1
Warm Up Method= 0
XS Weighting Method= 0
Number of US Weighted Cross Sections= 1
Number of DS Weighted Cross Sections= 1
Upstream XS Weight=0
Main XS Weight=1
Downstream XS Weight=0
Number of DS XS's Weighted with US Boundary= 1
Upstream Boundary Weight= 1
Weight of XSs Associated with US Boundary= 0
Number of US XS's Weighted with DS Boundary= 1
Downstream Boundary Weight= 0.5
Weight of XSs Associated with DS Boundary= 0.5
Percentile Method= 0
Sediment Output Level= 3
Mass or Volume Output= 0
Output Increment Type= 1
Profile and TS Output Increment= 1
Transport Output Increment 1
XS Output Flag= 0
XS Output Increment= 10
Read HDF5 Sediment Hotstart= 0
Sediment Hotstart Type= 0
Write Gradation File= 0
Read Gradation Hotstart= 0
Write HDF5 File= 1
Write Binary Output= 1
Write DSS Sediment File= 0
DSS Sediment Output Type= 1
SV Curve= 0
Specific Gage Flag= 0
Subcell Erosion Methods= 0
Subcell Deposition Methods= 0
Advection Scheme= 1
Matrix Solver= 0
Implicit Weighting Factor= 1
Maximum Outer Loop Convergence Iterations= 5
Convergence Maximum Absolute= 0.001
Convergence RMSE= 0.0001
Grain Fractions Max Abs Error= 0.001
Max Subgrid Regions= 1
Max Subgrid Length Scale= 3.402823E+38
Initial Layer Thickness= 3.402823E+38
Min Layer Thickness= 3.402823E+38
Max Layer Thickness= 3.402823E+38
Number of Layers= 5

--- ROBERTSRN.f01 (steady flow) ---

Flow Title=Flow
Program Version=6.30
Number of Profiles= 1
Profile Names=F01pct
River Rch & RM=ROBERTSRN,Main            ,2294
     661
Boundary for River Rch & Prof#=ROBERTSRN,Main            , 1
Up Type= 0
Dn Type= 3
Dn Slope=0.01388
DSS Import GetInterval= 0
DSS Import GetPeak= 0
DSS Import FillOption= 0

--- ROBERTSRN.g01 (geometry) ---

Geom Title=Geometry
Program Version=6.30

River Reach=ROBERTSRN       ,Main
Reach XY= 30
     1688782.676      420772.428     1688822.408      420772.837
     1688960.852      420794.546     1689018.606      420827.724
     1689188.999      420865.407     1689285.665      420861.721
     1689326.215      420868.274     1689486.368      420928.895
     1689641.529      420977.483     1689716.841      421013.024
     1689759.254      421046.329     1689758.993      421066.105
     1689730.632      421082.497     1689729.331      421096.288
     1689812.594      421130.8951689892.68358541421136.788784865
1689935.73402865421149.4049464891689959.97565189421176.953895676
     1690004.621      421206.352     1690125.614      421267.759
     1690134.461      421285.973     1690174.271       421320.84
     1690207.057      421331.248     1690273.408      421376.002
     1690343.922       421411.91     1690438.634      421493.612
     1690513.572      421531.601     1690598.397      421558.922
     1690716.007      421590.667     1690806.643      421604.344

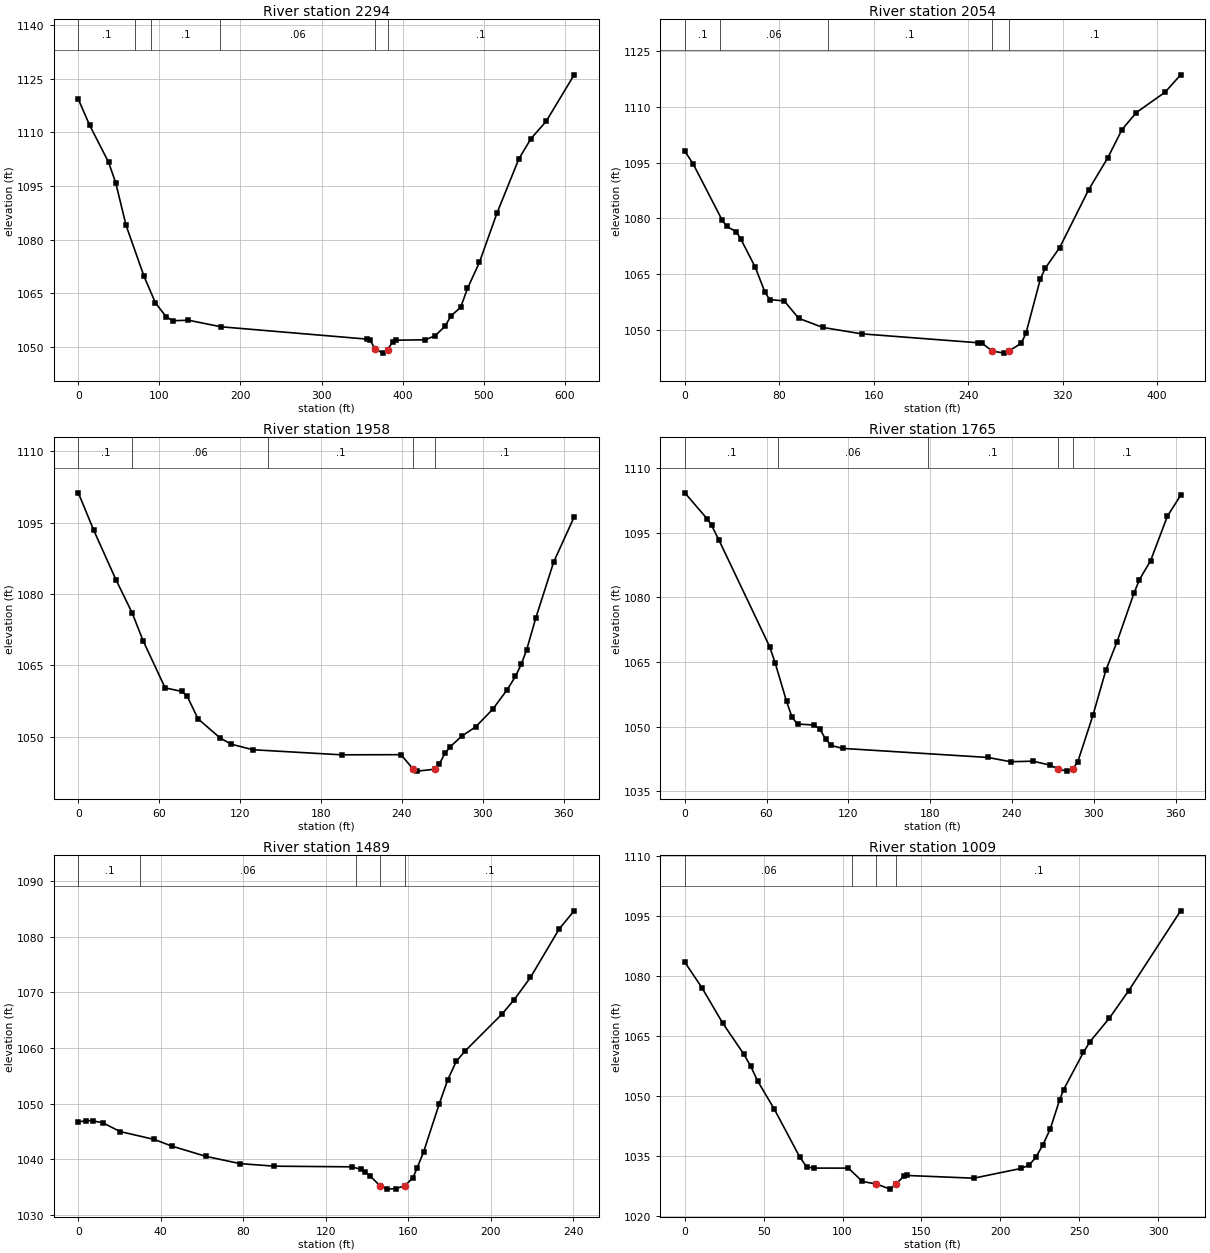
Type RM Length L Ch R = 1 ,2294    ,239.6,239.6,239.6
XS GIS Cut Line= 4
1688852.41481956 421135.301281071688804.21610211421053.363461403
1688817.06909343420664.5604739621688892.58041744420561.736543399
#Sta/Elev= 30
       0 1119.24    13.9 1111.99    37.3 1101.61    46.1 1095.88    58.9 1083.96
    81.1 1069.68    95.1 1062.29   108.4 1058.37   116.7 1057.29   135.9 1057.43
   175.9  1055.6     356 1052.15     360 1051.81   366.41049.295     376 1048.23
   381.6 1049.22     388 1051.45   392.1 1051.85   428.1 1051.96   440.1 1053.09
   452.1 1055.68   460.1 1058.74   471.6    1061   480.1 1066.31   494.9 1073.66
   516.3 1087.29   543.5 1102.57   558.5 1108.24   577.1 1113.03   611.7 1126.06
#Mann= 6 ,-1,0
       0      .1       0      70     .06       0      90      .1       0
  175.06     .06       0   366.4    .045       0   381.6      .1       0
Bank Sta=366.4,381.6
XS Rating Curve= 0 ,0
Exp/Cntr(USF)=0,0
Exp/Cntr=0.3,0.1

Type RM Length L Ch R = 1 ,2054    ,95.7,95.7,95.7
XS GIS Cut Line= 4
1688989.68604731421095.6572100661688997.88464915421034.753310695
1689056.44609085420765.3706788591689068.15837919420683.384660475
#Sta/Elev= 30
       0 1098.06     7.2 1094.55    31.4 1079.64    35.4  1077.8    43.5 1076.42
    47.5 1074.36    59.7 1066.83    67.8 1060.18    71.9 1058.13    84.2 1057.77
    96.5 1053.08   116.9 1050.64   149.7 1048.92   247.9 1046.53     252 1046.32
   260.2 1044.32   260.2 1044.31   270.3 1043.73   274.41044.309   284.8 1046.32
   288.9 1049.03   301.1 1063.66   305.2 1066.55   317.4 1072.08     342 1087.67
   358.2 1096.25   370.3 1103.87   382.4 1108.44   406.7 1113.89   419.9 1118.58
#Mann= 5 ,-1,0
       0      .1       0      30     .06       0  121.45      .1       0
   260.2    .045       0   274.4      .1       0
Bank Sta=260.2,274.4
XS Rating Curve= 0 ,0
Exp/Cntr(USF)=0,0
Exp/Cntr=0.3,0.1

Type RM Length L Ch R = 1 ,1958    ,193.7,193.7,193.7
XS GIS Cut Line= 4
1689087.10904328421107.7809173381689111.53944762420979.556970214
1689144.59095974420803.0955072491689141.22978901420745.395409835
#Sta/Elev= 30
       0 1101.26    11.4  1093.4      28 1082.93    39.9 1076.03    48.1 1070.12
    64.4 1060.23    76.6  1059.5    80.7 1058.51    88.8 1053.72   105.1 1049.72
   113.2 1048.41   129.5 1047.22   195.3 1046.15   239.4 1046.18   248.6  1043.1
   251.6 1042.72   264.31043.121   267.9 1044.24     272 1046.45     276 1047.88
   284.4 1050.05   294.7 1052.01   307.5 1055.74   318.3 1059.88   324.3 1062.63
   328.7 1065.22   332.7 1068.28   339.4  1074.9   352.7  1086.7   367.9 1096.19
#Mann= 5 ,-1,0
       0      .1       0      40     .06       0  140.53      .1       0
   248.6    .045       0   264.3      .1       0
Bank Sta=248.6,264.3
XS Rating Curve= 0 ,0
Exp/Cntr(USF)=0,0
Exp/Cntr=0.3,0.1

Type RM Length L Ch R = 1 ,1765    ,275.5,275.5,275.5
XS GIS Cut Line= 3
1689260.02752475421140.5686361441689277.87890159421074.518541858
1689345.71413356420787.111374833
#Sta/Elev= 30
       0 1104.26    16.6 1098.15    19.7 1096.68    24.9 1093.39    62.2 1068.57
    66.3 1064.74    74.6 1055.88    78.7  1052.1    82.8 1050.57    95.1 1050.35
    99.2 1049.32   103.3 1047.07   107.4  1045.6   115.7 1044.92   222.5 1042.81
     239 1041.82   255.4 1041.95   267.7 1041.05   273.81040.148   280.1 1039.64
   284.7 1040.16   288.3 1041.85   299.4 1052.62   308.8 1063.01   317.1 1069.72
   329.4 1080.89   333.5 1084.11   341.7 1088.52     354 1098.83   363.7 1103.69
#Mann= 5 ,-1,0
       0      .1       0   68.42     .06       0  178.42      .1       0
   273.8    .045       0   284.7      .1       0
Bank Sta=273.8,284.7
XS Rating Curve= 0 ,0
Exp/Cntr(USF)=0,0
Exp/Cntr=0.3,0.1

Type RM Length L Ch R = 1 ,1489    ,480.3,480.3,480.3
XS GIS Cut Line= 4
1689543.04500381421104.0095604921689571.50586447421003.447852799
1689603.76150656420905.7322311731689624.63280439420880.117456572
#Sta/Elev= 30
       0 1046.71     3.6 1046.97     6.9 1046.94    11.9 1046.57    20.2 1045.01
    36.9 1043.58    45.2 1042.41    61.8 1040.56    78.4 1039.25    95.1 1038.79
   132.9 1038.67   137.1  1038.2     139 1037.74   141.3 1037.11   146.31035.283
   149.7 1034.67   153.9 1034.75   158.4 1035.28   162.3 1036.72   164.3 1038.43
   167.5 1041.38     175 1049.91   179.2 1054.31   183.3 1057.59   187.6 1059.46
   205.5 1066.09   211.4 1068.67   219.3 1072.66   233.3  1081.4   240.5 1084.62
#Mann= 5 ,-1,0
       0      .1       0      30     .06       0  134.51      .1       0
   146.3    .045       0   158.4      .1       0
Bank Sta=146.3,158.4
XS Rating Curve= 0 ,0
Exp/Cntr(USF)=0,0
Exp/Cntr=0.3,0.1

Type RM Length L Ch R = 1 ,1009    ,280.3,280.3,280.3
XS GIS Cut Line= 5
 1689878.1750634421266.2669814421689910.85234787 421197.75009465
 1689957.2330097421098.6641352871689981.47744657421043.850625853
1689996.23492988420976.387845011
#Sta/Elev= 30
       0 1083.47    10.8 1077.13    24.1 1068.22    37.4 1060.53    41.8 1057.49
    46.2  1053.8    56.8 1046.75    72.8 1034.88    77.2 1032.41    81.7 1032.08
   103.7 1032.07   112.6 1028.74   121.4 1028.11   130.2 1026.83   133.9 1028.16
   139.1 1030.11   140.9 1030.24   183.1 1029.56   213.4 1032.01   218.3 1032.86
   222.5 1034.75     227 1037.89   231.6 1041.79   237.6  1049.1   240.1 1051.66
   252.7 1060.97   256.8 1063.61   269.1 1069.49   281.4 1076.37   314.3 1096.29
#Mann= 4 ,-1,0
       0     .06       0  105.91      .1       0   121.4    .045       0
   133.9      .1       0
Bank Sta=121.4,133.9
XS Rating Curve= 0 ,0
Exp/Cntr(USF)=0,0
Exp/Cntr=0.3,0.1

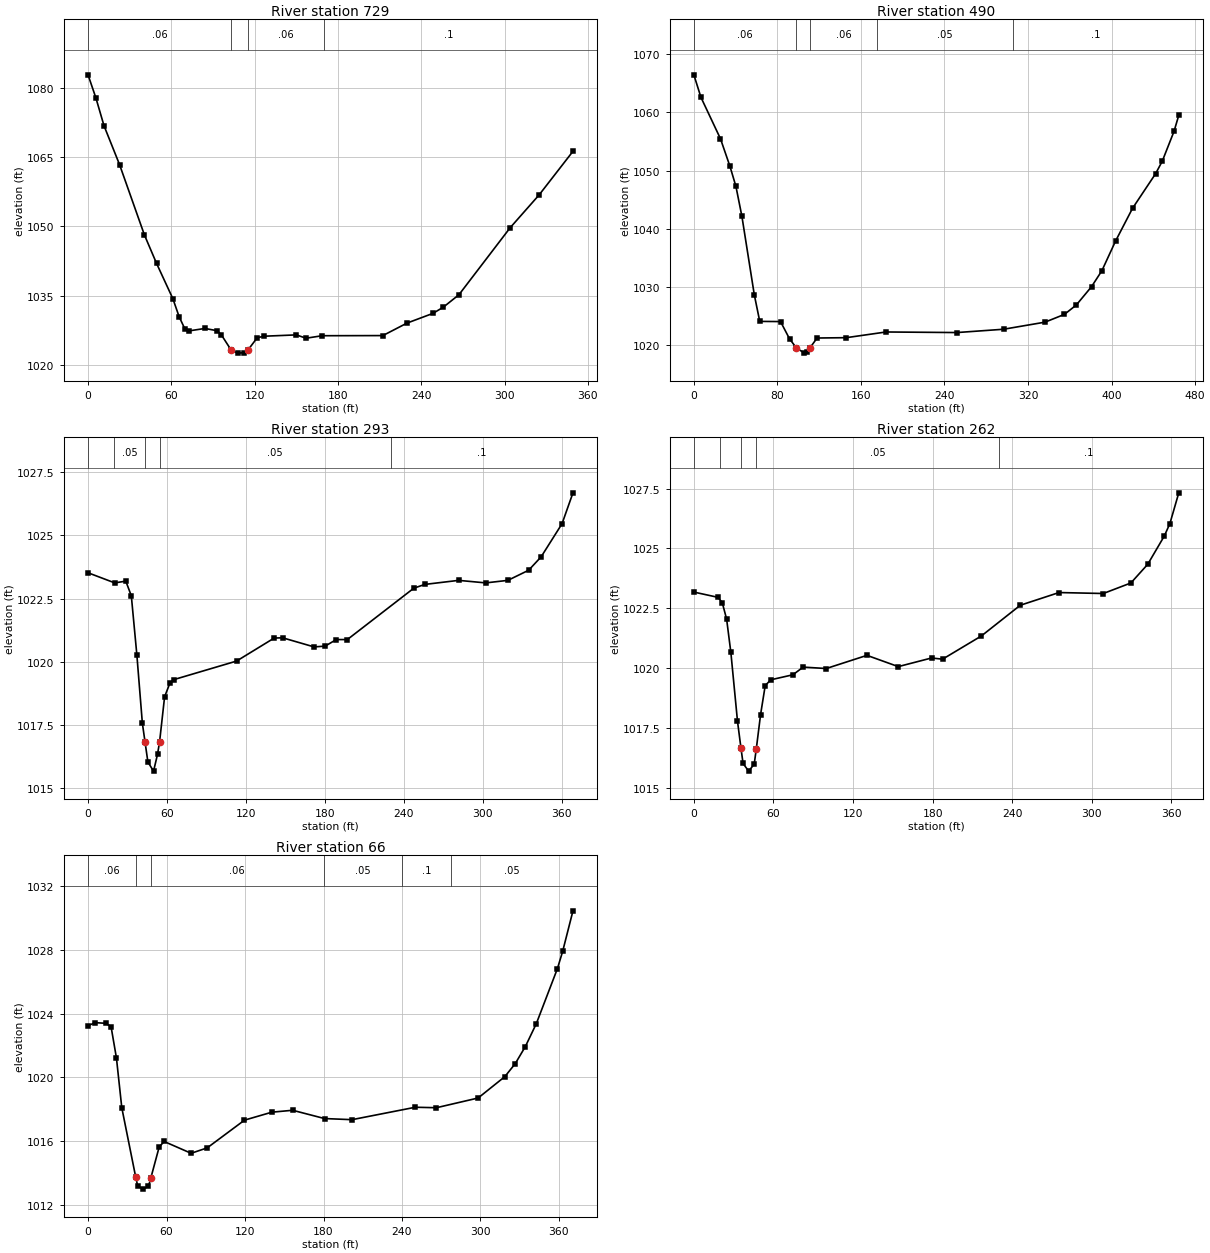
Type RM Length L Ch R = 1 ,729     ,238.9,238.9,238.9
XS GIS Cut Line= 3
1690100.25820284421400.491920257 1690239.0705091421173.475961061
1690257.86800891421092.502115742
#Sta/Elev= 30
       0 1082.76     5.7 1077.73    11.5 1071.76    22.7 1063.36    40.6 1048.17
    49.3 1042.05    61.1 1034.39    65.6  1030.5    69.7 1027.89    72.6 1027.44
    84.2 1027.97      93 1027.48    95.9 1026.64   103.1 1023.28   107.8 1022.64
   112.5 1022.74     115 1023.25   121.8 1025.95   126.5 1026.29     150 1026.58
     157 1025.86   168.6  1026.4   212.3 1026.43   229.7 1029.13   248.4 1031.23
   255.9 1032.58   267.1 1035.26     304 1049.74   324.8 1056.81   349.2 1066.24
#Mann= 4 ,-1,0
       0     .06       0   103.1    .045       0     115     .06       0
     170      .1       0
Bank Sta=103.1,115
XS Rating Curve= 0 ,0
Exp/Cntr(USF)=0,0
Exp/Cntr=0.3,0.1

Type RM Length L Ch R = 1 ,490     ,197.1,197.1,197.1
XS GIS Cut Line= 4
 1690287.7258453421500.8861058361690338.08868517421458.721867809
1690532.76198924 421193.301573571690546.04372422421124.995507967
#Sta/Elev= 30
       0 1066.47     6.8 1062.59    25.5 1055.46    34.6 1050.71    40.3 1047.26
      46 1042.13    57.9  1028.6    63.1 1024.04      83 1024.01    91.6 1021.05
    98.2 1019.47   105.9 1018.58   108.8 1018.77   111.21019.492     118 1021.18
     146 1021.24   184.1 1022.22   251.9 1022.12   296.6 1022.69   336.3 1023.91
   354.9 1025.25   366.3 1026.87   380.9 1030.03   390.8 1032.78   403.8 1037.85
   420.1  1043.5   442.2 1049.46   448.6 1051.62   459.8 1056.73   464.4 1059.51
#Mann= 5 ,-1,0
       0     .06       0    98.2    .045       0   111.2     .06       0
  175.68     .05       0  305.68      .1       0
Bank Sta=98.2,111.2
XS Rating Curve= 0 ,0
Exp/Cntr(USF)=0,0
Exp/Cntr=0.3,0.1

Type RM Length L Ch R = 1 ,293     ,30.8,30.8,30.8
XS GIS Cut Line= 2
1690508.82165419421579.818038947 1690623.5920671421229.527458019
#Sta/Elev= 30
       0 1023.52    20.3 1023.12    28.7 1023.19    32.9 1022.61    37.1 1020.28
    41.3 1017.57    43.3 1016.84    45.5 1016.04    49.8 1015.68    52.8 1016.34
    54.41016.847    58.2 1018.62    62.4 1019.18    65.4  1019.3   112.9 1020.03
   141.5 1020.94   147.9 1020.95   171.8 1020.59   180.2 1020.62   188.7 1020.88
   197.1 1020.88   247.6 1022.91     256 1023.06   281.7 1023.22   302.3 1023.12
   319.1 1023.22   334.9 1023.62   344.4 1024.15   360.3 1025.46   368.6 1026.68
#Mann= 5 ,-1,0
       0     .06       0      20     .05       0    43.3    .045       0
    54.4     .05       0     230      .1       0
Bank Sta=43.3,54.4
XS Rating Curve= 0 ,0
Exp/Cntr(USF)=0,0
Exp/Cntr=0.3,0.1

Type RM Length L Ch R = 1 ,262     ,195.8,195.8,195.8
XS GIS Cut Line= 2
1690540.88375189421584.0422631341690646.73074682421234.138117448
#Sta/Elev= 30
       0 1023.18    18.2 1022.96    21.4 1022.74    24.7 1022.05    27.9 1020.66
    32.9 1017.79    35.51016.677    37.1 1016.03    41.3 1015.71    45.5    1016
    47.1 1016.65    50.3 1018.07    53.8 1019.28      58 1019.52    74.7 1019.73
    82.4 1020.05    99.8 1019.99   130.5 1020.54   154.1 1020.07   179.2 1020.43
   187.5 1020.38   216.8 1021.35   246.1 1022.63   275.3 1023.16   308.7 1023.12
   329.5 1023.56   342.2 1024.34   354.7 1025.52   358.9 1026.04   365.6 1027.32
#Mann= 5 ,-1,0
       0     .06       0      20     .05       0    35.5    .045       0
    47.1     .05       0     230      .1       0
Bank Sta=35.5,47.1
XS Rating Curve= 0 ,0
Exp/Cntr(USF)=0,0
Exp/Cntr=0.3,0.1

Type RM Length L Ch R = 1 ,66      ,,,
XS GIS Cut Line= 3
1690732.91447224421637.8245955791690781.74391731421394.929797303
1690768.51295472421272.706924562
#Sta/Elev= 30
       0 1023.25     5.4 1023.44    13.6  1023.4    17.6 1023.19    21.7 1021.23
    25.8  1018.1    36.51013.722      38 1013.18    42.1 1012.99    46.2 1013.17
      48 1013.69    54.4 1015.64    58.2 1015.98    78.8 1015.24    91.1 1015.58
   119.6 1017.32   140.5 1017.82   156.4 1017.94   180.8 1017.42   201.8 1017.35
   250.2 1018.13   266.3  1018.1   298.2 1018.71   318.6 1020.05   326.6 1020.87
   334.3 1021.94   342.7 1023.38   358.8 1026.83   362.8 1027.91   370.7 1030.46
#Mann= 6 ,-1,0
       0     .06       0    36.5    .045       0      48     .06       0
     180     .05       0     240      .1       0  277.75     .05       0
Bank Sta=36.5,48
XS Rating Curve= 0 ,0
Exp/Cntr(USF)=0,0
Exp/Cntr=0.3,0.1
LCMann Table=0

Chan Stop Cuts=-1
Use User Specified Reach Order=0
Composite Channel Slope=5